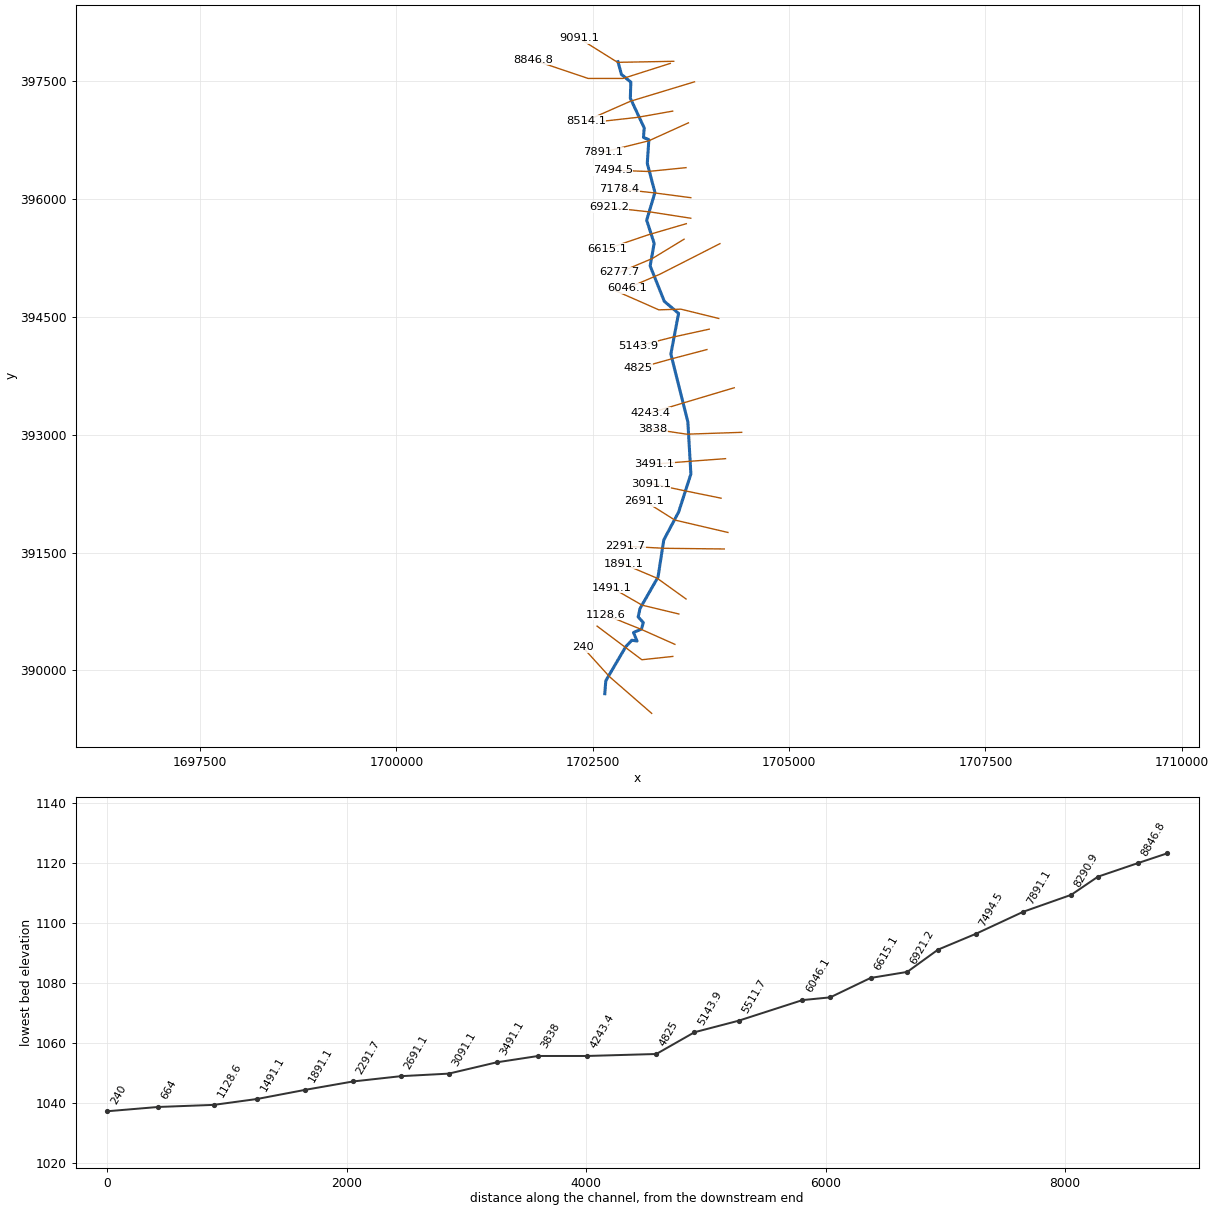
--- TrbBRTHFK.prj (project) ---

Proj Title=TrbBRTHFK
Current Plan=p01
Geom File=g01
Flow File=f01
Plan File=p01
DSS Export Rating Curves=0
DSS Export Rating Curve Sorted=0
DSS Export Volume Flow Curves=0
DXF OffsetX=0
DXF OffsetY=0
DXF ScaleX=0
DXF ScaleY=0

--- TrbBRTHFK.p01 (plan) ---

Plan Title=Floodplain
Program Version=4.00
Geom File=g01
Flow File=f01
K Sum by GR=0
Std Step Tol=0.01
Critical Tol=0.01
Num of Std Step Trials=20
Max Error Tol=0.3
Flow Tol Ratio=0.001
Split Flow NTrial=30
Split Flow Tol=0.02
Split Flow Ratio=0.02
Log Output Level=0
Friction Slope Method=1
Unsteady Friction Slope Method=2
Unsteady Bridges Friction Slope Method=1
Global Log Level=0
CheckData=False
Run HTab=0
Run UNet=0
Run PostProcess=0
UNET Theta=0
UNET Theta Warmup=0
UNET ZTol=0
UNET ZSATol=0
UNET MxIter=0
UNET MaxInSteps=0
UNET DtIC=0
UNET DtMin=0
UNET MaxCRTS=0
UNET WFStab=0
UNET SFStab=0
UNET WFX=0
UNET SFX=0
UNET DSS MLevel=0
UNET DZMax Abort=0
UNET Convert EG Bridges=0
UNET Use Existing IB Tables=0
UNET Froude Limit=0
UNET Froude Power=0
Write IC File=0
Echo Input=False
Echo Output=False
Write Detailed=0

--- TrbBRTHFK.f01 (steady flow) ---

Flow Title=NFF Regression Equation
Program Version=4.00
Number of Profiles=1
Profile Names=P100yr
River Rch & RM=TrbBRTHFK,Main      ,9091.1
393.5328
River Rch & RM=TrbBRTHFK,Main      ,8514.1
431.2680
River Rch & RM=TrbBRTHFK,Main      ,8290.9
449.3093
River Rch & RM=TrbBRTHFK,Main      ,6921.2
495.1731
River Rch & RM=TrbBRTHFK,Main      ,6615.1
558.9948
River Rch & RM=TrbBRTHFK,Main      ,5511.7
574.1792
River Rch & RM=TrbBRTHFK,Main      ,5143.9
1086.566
River Rch & RM=TrbBRTHFK,Main      ,4243.4
1140.782
River Rch & RM=TrbBRTHFK,Main      ,240
1264.845
Boundary for River Rch & Prof#=TrbBRTHFK,Main      ,1
Up Type=0
Dn Type=3
Dn Slope=0.005442

--- TrbBRTHFK.g01 (geometry) ---

Geom Title=USGS 3m DEM
Program Version=4.00

River Reach=TrbBRTHFK     ,Main
Reach XY= 30
     1702822.144      397750.103     1702866.456      397587.392
     1702986.058      397490.207     1702979.508      397284.674
     1703156.409      396906.546     1703147.014      396785.555
     1703215.597      396756.442     1703195.166      396456.955
     1703292.895      396084.298     1703187.706      395731.476
     1703283.135      395436.699     1703232.024      395149.381
     1703412.293      394698.554     1703593.696      394545.034
     1703495.422      394026.962     1703711.896      393164.312
     1703750.557      392500.514     1703594.749      392016.933
     1703405.248      391660.351     1703331.867      391187.512
     1703103.585      390788.716     1703079.200      390680.584
     1703145.267      390608.203     1703121.062      390526.204
     1703019.886      390481.895     1703065.205      390373.398
     1702999.532      390384.162     1702920.820      390300.842
     1702666.972      389867.512     1702654.516      389702.955

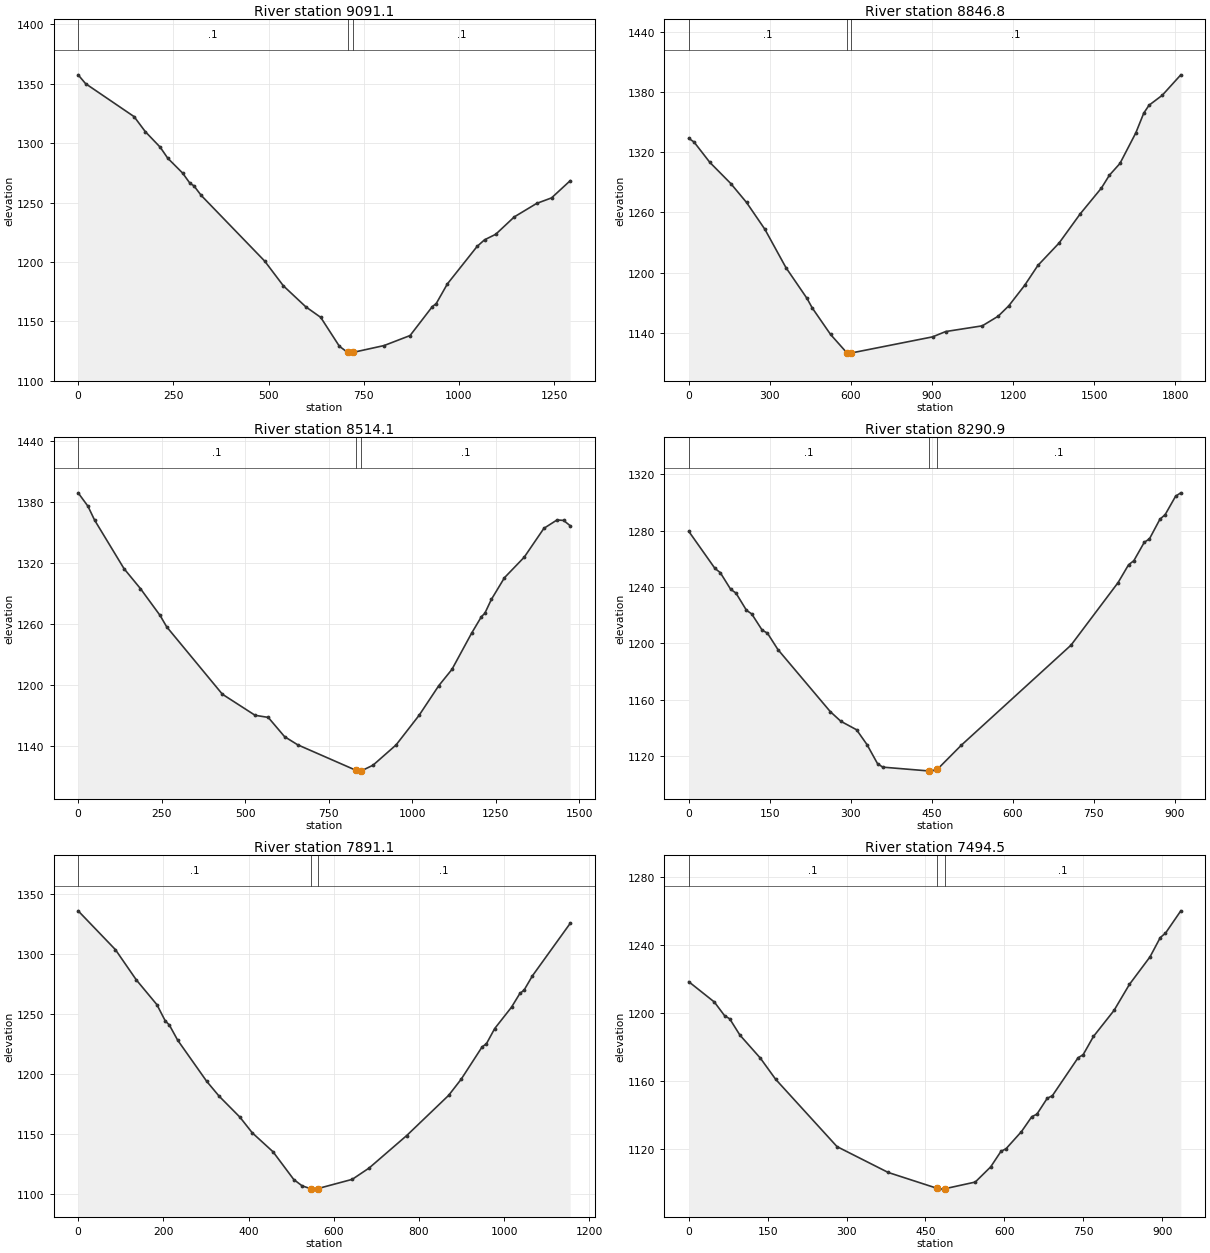
Type RM Length L Ch R = 1 ,9091.1,241.152,244.338,262.123
XS GIS Cut Line= 3
     1703532.136      397754.887     1702816.888      397741.596
     1702327.721      398047.221
#Sta/Elev= 30
       0 1357.55    19.6 1350.11   147.0 1322.34   176.4 1309.71   215.6 1296.57
   235.2 1287.39   274.4 1274.81   294.0 1266.07   303.8 1264.17   323.4 1255.94
   490.0 1200.67   539.0 1179.86   597.8 1162.20   637.0 1153.32   686.0 1129.00
   707.9 1123.74   715.4 1123.18   722.9 1123.87   803.4 1129.55   871.8 1138.00
   930.4 1162.44   940.2 1164.80   969.6 1181.42  1047.8 1213.04  1067.3 1218.61
  1096.6 1223.25  1145.5 1237.92  1204.2 1249.26  1243.3 1253.91  1292.2 1268.37
#Mann= 3 , 0 , 0
       0     0.1       0   707.9   0.045       0   722.9     0.1       0
Bank Sta=   707.9,   722.9
Exp/Cntr=0.3,0.1

Type RM Length L Ch R = 1 ,8846.8,329.711,332.66,336.714
XS GIS Cut Line= 4
     1703488.541      397728.173     1702886.883      397536.562
     1702442.346      397536.562     1701737.218      397774.160
#Sta/Elev= 30
       0 1333.67    19.4 1330.06    77.7 1309.83   155.4 1288.70   213.7 1269.87
   281.7 1243.10   359.4 1205.03   437.1 1174.49   456.6 1164.95   524.6 1138.47
   584.1 1120.45   592.6 1119.93   599.1 1119.97   902.0 1136.13   950.3 1141.41
  1085.8 1147.10  1144.5 1156.68  1183.7 1167.02  1242.4 1187.39  1291.4 1207.22
  1369.7 1229.47  1448.0 1258.55  1526.3 1284.19  1555.7 1296.93  1594.9 1308.68
  1653.6 1339.11  1683.0 1358.78  1702.6 1366.68  1751.5 1376.57  1820.1 1396.91
#Mann= 3 , 0 , 0
       0     0.1       0   584.1   0.045       0   599.1     0.1       0
Bank Sta=   584.1,   599.1
Exp/Cntr=0.3,0.1

Type RM Length L Ch R = 1 ,8514.1,225.903,223.181,218.075
XS GIS Cut Line= 3
     1703797.373      397493.819     1702980.385      397246.019
     1702413.285      396996.248
#Sta/Elev= 30
       0 1388.69    29.4 1375.52    49.1 1362.00   137.4 1314.23   186.4 1294.71
   245.3 1268.31   265.0 1257.17   431.8 1190.98   529.9 1170.24   569.2 1168.18
   618.2 1149.26   657.5 1141.26   832.9 1116.10   843.9 1115.42   847.9 1115.66
   883.2 1121.28   952.1 1141.16  1021.0 1170.23  1080.0 1199.37  1119.3 1215.29
  1178.3 1250.91  1207.8 1267.18  1217.7 1270.30  1237.3 1283.95  1276.7 1305.37
  1335.7 1325.45  1394.7 1353.81  1434.1 1362.07  1453.7 1361.59  1473.4 1356.41
#Mann= 3 , 0 , 0
       0     0.1       0   832.9   0.045       0   847.9     0.1       0
Bank Sta=   832.9,   847.9
Exp/Cntr=0.3,0.1

Type RM Length L Ch R = 1 ,8290.9,392.328,399.822,400.668
XS GIS Cut Line= 3
     1703518.536      397120.524     1703069.395      397040.855
     1702617.400      396990.457
#Sta/Elev= 30
       0 1279.48    48.5 1253.16    58.2 1250.26    77.6 1238.34    87.3 1235.74
   106.8 1223.48   116.5 1220.92   135.9 1209.38   145.6 1207.28   165.0 1195.64
   262.0 1151.58   281.5 1144.75   310.6 1138.73   330.0 1128.17   349.4 1114.70
   359.1 1112.21   444.9 1109.48   446.4 1109.38   459.9 1110.55   504.5 1127.76
   707.7 1198.78   794.8 1243.17   814.2 1255.80   823.9 1258.64   843.2 1271.68
   852.9 1274.21   872.2 1288.08   881.9 1291.34   901.3 1304.45   910.9 1306.82
#Mann= 3 , 0 , 0
       0     0.1       0   444.9   0.045       0   459.9     0.1       0
Bank Sta=   444.9,   459.9
Exp/Cntr=0.3,0.1

Type RM Length L Ch R = 1 ,7891.1,405.278,396.56,390.689
XS GIS Cut Line= 3
     1703719.230      396971.433     1703213.904      396742.441
     1702631.748      396597.246
#Sta/Elev= 30
       0 1336.23    87.6 1303.76   136.3 1278.65   184.9 1257.82   204.4 1244.33
   214.1 1240.82   233.6 1228.17   301.7 1193.82   330.9 1181.39   379.6 1163.91
   408.8 1150.74   457.5 1134.92   506.1 1111.77   525.6 1106.51   547.3 1103.91
   554.8 1103.75   562.3 1104.18   643.3 1111.92   682.7 1121.32   771.2 1148.53
   869.5 1182.06   899.0 1195.57   948.2 1222.61   958.1 1225.11   977.7 1237.90
  1017.1 1255.73  1036.7 1267.18  1046.6 1270.00  1066.3 1281.98  1154.8 1325.74
#Mann= 3 , 0 , 0
       0     0.1       0   547.3   0.045       0   562.3     0.1       0
Bank Sta=   547.3,   562.3
Exp/Cntr=0.3,0.1

Type RM Length L Ch R = 1 ,7494.5,323.059,316.175,310.1
XS GIS Cut Line= 3
     1703689.169      396400.800     1703205.667      396352.130
     1702756.459      396368.393
#Sta/Elev= 30
       0 1218.43    48.6 1206.49    68.0 1198.48    77.8 1196.61    97.2 1187.03
   136.1 1173.46   165.2 1161.00   281.8 1121.41   379.0 1106.21     472 1096.87
   476.2 1096.39     487 1096.64   544.6 1100.55   573.9 1109.47   593.4 1118.58
   603.2 1120.18   632.5 1130.26   652.1 1139.01   661.8 1140.49   681.4 1149.83
   691.2 1151.36   740.0 1173.65   749.8 1175.53   769.3 1186.22   808.4 1201.53
   837.7 1216.86   876.8 1233.04   896.4 1244.45   906.1 1246.94   935.4 1260.15
#Mann= 3 , 0 , 0
       0     0.1       0     472   0.045       0     487     0.1       0
Bank Sta=     472,     487
Exp/Cntr=0.3,0.1

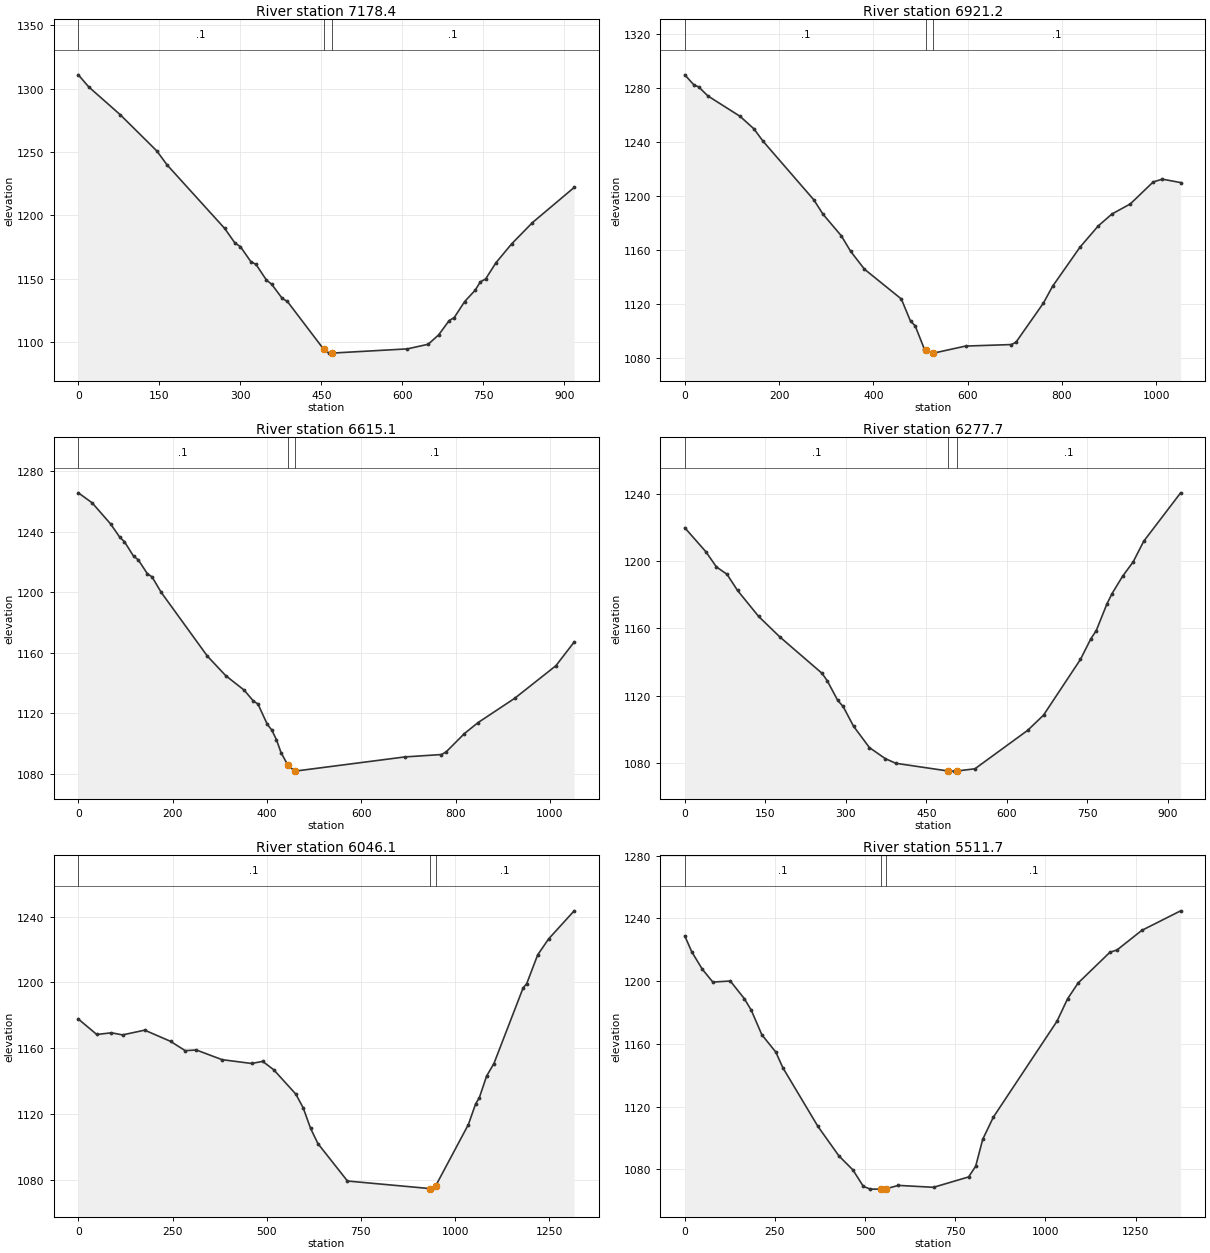
Type RM Length L Ch R = 1 ,7178.4,256.779,257.193,257.808
XS GIS Cut Line= 3
     1703749.556      396018.339     1703288.834      396078.995
     1702837.776      396128.812
#Sta/Elev= 30
       0 1310.84    19.4 1301.25    77.4 1279.44   145.2 1250.84   164.6 1239.64
   271.1 1189.57   290.4 1177.90   300.1 1175.29   319.5 1163.39   329.2 1161.15
   348.5 1148.78   358.2 1145.51   377.6 1134.39   387.2 1131.95   454.2 1094.36
   464.7 1091.12   469.2 1091.13   609.5 1094.47   648.1 1098.12   667.5 1105.53
   686.8 1116.75   696.4 1119.24   715.7 1131.87   735.0 1140.71   744.7 1147.39
   754.4 1149.63   773.7 1162.51   802.6 1177.34   841.3 1194.20   918.5 1221.92
#Mann= 3 , 0 , 0
       0     0.1       0   454.2   0.045       0   469.2     0.1       0
Bank Sta=   454.2,   469.2
Exp/Cntr=0.3,0.1

Type RM Length L Ch R = 1 ,6921.2,297.092,306.095,314.487
XS GIS Cut Line= 3
     1703749.294      395756.775     1703247.240      395834.687
     1702706.924      395894.195
#Sta/Elev= 30
       0 1289.50    19.5 1281.99    29.3 1280.63    48.9 1273.92   117.2 1258.81
   146.6 1249.56   166.1 1240.35   273.6 1197.08   293.1 1186.44   332.2 1170.34
   351.7 1159.01   381.0 1145.78   459.2 1123.76   478.8 1107.28   488.5 1103.97
   508.1 1086.71   512.4 1085.76   527.4 1083.70   595.4 1088.91   692.5 1090.04
   702.2 1091.67   760.4 1120.62   779.9 1133.06   838.1 1162.03   876.9 1177.77
   906.0 1186.60   944.9 1194.04   993.4 1210.28  1012.8 1212.35  1051.6 1209.83
#Mann= 3 , 0 , 0
       0     0.1       0   512.4   0.045       0   527.4     0.1       0
Bank Sta=   512.4,   527.4
Exp/Cntr=0.3,0.1

Type RM Length L Ch R = 1 ,6615.1,332.424,337.355,340.861
XS GIS Cut Line= 3
     1703692.393      395687.344     1703204.722      395544.845
     1702690.215      395369.444
#Sta/Elev= 30
       0 1265.77    29.3 1259.16    68.4 1245.21    87.9 1236.40    97.7 1233.50
   117.2 1223.85   127.0 1221.52   146.6 1212.16   156.3 1210.20   175.9 1199.88
   273.6 1157.80   312.7 1144.81   351.7 1135.27   371.3 1128.04   381.0 1126.09
   400.6 1112.73   410.4 1108.83   420.1 1102.55   429.9 1093.95   444.8 1085.43
   459.2 1081.69   459.8 1081.70   692.5 1091.08   770.1 1092.67   779.9 1094.34
   818.7 1106.49   847.8 1113.80   925.5 1129.86  1012.8 1151.39  1051.6 1167.07
#Mann= 3 , 0 , 0
       0     0.1       0   444.8   0.045       0   459.8     0.1       0
Bank Sta=   444.8,   459.8
Exp/Cntr=0.3,0.1

Type RM Length L Ch R = 1 ,6277.7,233.985,231.665,230.769
XS GIS Cut Line= 3
     1703664.089      395490.079     1703261.180      395244.599
     1702844.444      395069.276
#Sta/Elev= 30
       0 1219.85    39.3 1205.58    59.0 1196.55    78.6 1192.21    98.3 1182.58
   137.6 1167.15   176.9 1155.03   255.6 1133.39   265.4 1128.95   285.0 1117.22
   294.9 1113.68   314.5 1101.89   344.0 1089.22   373.5 1082.67   393.2 1079.88
   491.3 1075.27   501.3 1075.22   506.3 1075.27   540.6 1076.61   638.9 1099.46
   668.4 1108.48   737.2 1141.60   756.8 1153.96   766.7 1158.73   786.3 1174.38
   796.1 1180.72   815.8 1191.05   835.5 1199.59   855.1 1211.81   923.9 1240.60
#Mann= 3 , 0 , 0
       0     0.1       0   491.3   0.045       0   506.3     0.1       0
Bank Sta=   491.3,   506.3
Exp/Cntr=0.3,0.1

Type RM Length L Ch R = 1 ,6046.1,542.936,534.353,525.771
XS GIS Cut Line= 3
     1704120.355      395433.187     1703353.159      395042.535
     1702935.141      394863.265
#Sta/Elev= 30
       0 1177.73    48.9 1168.34    88.0 1169.36   117.4 1168.08   176.1 1170.97
   244.6 1164.18   283.7 1158.49   313.1 1158.91   381.5 1153.02   459.8 1150.71
   489.2 1151.98   518.5 1146.90   577.2 1132.08   596.8 1123.69   616.3 1111.27
   635.9 1101.97   714.2 1079.24   933.3 1074.64   938.3 1074.31   948.3 1076.30
  1035.1 1113.60  1054.5 1126.25  1064.2 1129.95  1083.5 1143.09  1102.9 1150.69
  1180.3 1196.63  1190.0 1199.30  1219.0 1216.75  1248.0 1226.44  1315.8 1243.52
#Mann= 3 , 0 , 0
       0     0.1       0   933.3   0.045       0   948.3     0.1       0
Bank Sta=   933.3,   948.3
Exp/Cntr=0.3,0.1

Type RM Length L Ch R = 1 ,5511.7,362.672,367.825,385.838
XS GIS Cut Line= 4
     1704105.110      394480.750     1703624.143      394598.902
     1703342.309      394590.464     1702795.455      394831.551
#Sta/Elev= 30
       0 1228.80    19.4 1218.66    48.6 1207.59    77.7 1199.41   126.2 1200.08
   165.1 1188.83   184.5 1181.39   213.6 1165.85   252.5 1154.74   271.9 1144.81
   369.0 1107.47   427.3 1088.63   466.1 1079.69   495.3 1069.14   514.7 1067.43
   543.1 1067.45   558.1 1067.69   592.5 1069.81   689.7 1068.59   787.0 1075.20
   806.6 1082.04   826.2 1099.22   855.6 1113.32  1032.0 1174.43  1061.4 1188.73
  1090.7 1198.83  1178.9 1218.43  1198.5 1219.86  1267.1 1232.34  1374.9 1244.82
#Mann= 3 , 0 , 0
       0     0.1       0   543.1   0.045       0   558.1     0.1       0
Bank Sta=   543.1,   558.1
Exp/Cntr=0.3,0.1

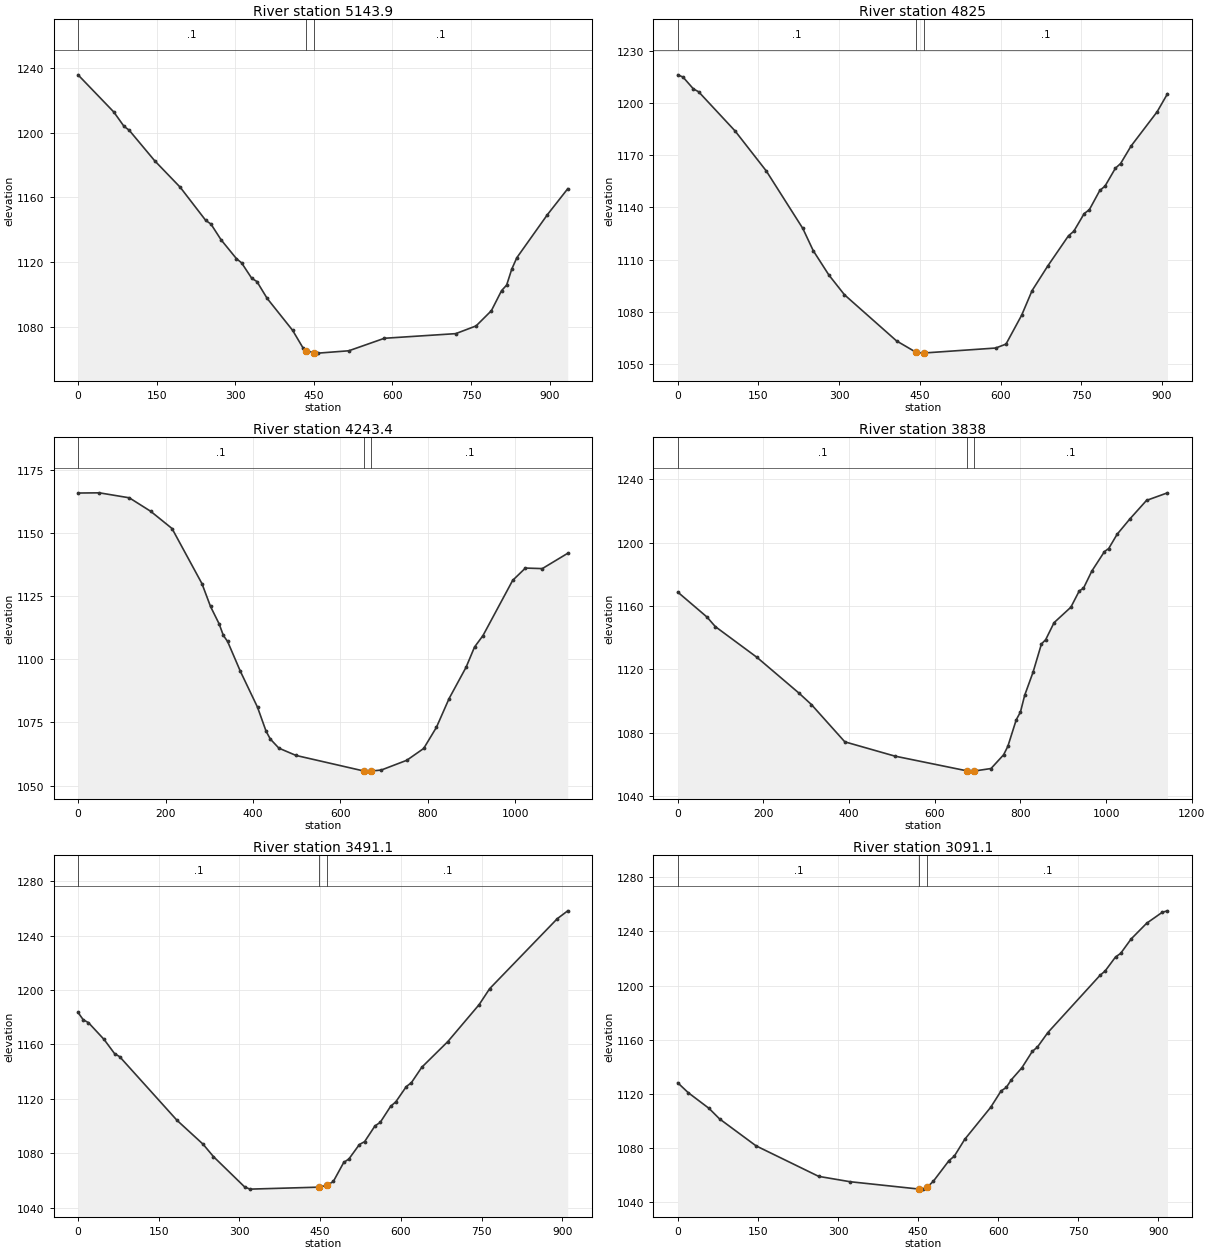
Type RM Length L Ch R = 1 ,5143.9,318.128,318.903,307.091
XS GIS Cut Line= 3
     1703984.471      394344.343     1703517.560      394242.341
     1703074.742      394130.113
#Sta/Elev= 30
       0 1235.73    68.3 1212.73    87.8 1203.86    97.5 1201.52   146.3 1182.59
   195.1 1166.17   243.8 1145.66   253.6 1143.47   273.1 1133.67   302.4 1122.02
   312.1 1119.47   331.6 1109.87   341.4 1107.89   360.9 1097.49   409.6 1077.69
   429.2 1066.95     436 1065.21     451 1063.71   458.4 1063.60   516.8 1065.05
   584.8 1072.79   720.9 1075.65   759.8 1080.44   788.9 1089.82   808.4 1102.25
   818.1 1105.69   827.8 1115.52   837.5 1122.60   895.9 1149.25   934.7 1165.28
#Mann= 3 , 0 , 0
       0     0.1       0     436   0.045       0     451     0.1       0
Bank Sta=     436,     451
Exp/Cntr=0.3,0.1

Type RM Length L Ch R = 1 ,4825,580.832,581.622,582.207
XS GIS Cut Line= 3
     1703955.154      394084.766     1703515.036      393969.118
     1703076.719      393847.078
#Sta/Elev= 30
       0 1216.18     9.7 1214.90    29.0 1208.11    38.7 1206.46   106.5 1183.94
   164.6 1160.92   232.4 1127.93   251.7 1115.21   280.8 1101.21   309.8 1089.85
   406.6 1063.36     443 1056.79   455.1 1056.35     458 1056.44   590.6 1059.27
   609.9 1061.53   639.0 1078.12   658.4 1092.27   687.4 1106.34   726.1 1123.78
   735.8 1126.29   755.2 1136.48   764.8 1138.73   784.2 1149.76   793.9 1152.26
   813.2 1162.54   822.9 1165.24   842.3 1175.27   890.7 1194.93   910.0 1205.31
#Mann= 3 , 0 , 0
       0     0.1       0     443   0.045       0     458     0.1       0
Bank Sta=     443,     458
Exp/Cntr=0.3,0.1

Type RM Length L Ch R = 1 ,4243.4,411.101,405.305,398.758
XS GIS Cut Line= 3
     1704302.377      393598.378     1703665.769      393408.392
     1703230.073      393276.793
#Sta/Elev= 30
       0 1165.76    48.8 1165.84   117.2 1163.87   166.1 1158.53   214.9 1151.71
   283.3 1129.90   302.9 1120.85   322.4 1114.04   332.2 1109.40   341.9 1107.01
   371.3 1095.13   410.3 1080.99   429.9 1071.48   439.6 1068.38   459.2 1064.78
   498.3 1061.90   654.6 1055.69   669.6 1055.70   693.4 1056.13   751.5 1059.98
   790.2 1064.66   819.3 1073.02   848.3 1084.43   887.1 1096.81   906.4 1104.80
   925.8 1109.36   993.6 1131.19  1022.7 1136.06  1061.4 1135.85  1119.5 1141.92
#Mann= 3 , 0 , 0
       0     0.1       0   654.6   0.045       0   669.6     0.1       0
Bank Sta=   654.6,   669.6
Exp/Cntr=0.3,0.1

Type RM Length L Ch R = 1 ,3838,346.027,346.949,348.657
XS GIS Cut Line= 3
     1704397.444      393030.775     1703695.843      393007.388
     1703259.320      393073.002
#Sta/Elev= 30
       0 1168.80    68.2 1153.05    87.7 1147.00   185.2 1127.51   282.7 1105.05
   312.0 1097.77   390.0 1074.20   507.0 1065.17   675.7 1055.84   690.7 1055.69
   731.4 1057.34   760.8 1066.02   770.7 1071.38   790.3 1088.16   800.1 1093.03
   809.9 1103.55   829.5 1118.19   849.1 1136.03   858.9 1138.70   878.6 1149.50
   917.8 1159.26   937.4 1169.55   947.2 1171.21   966.8 1182.11   996.3 1194.43
  1006.1 1196.31  1025.7 1205.30  1055.1 1214.87  1094.4 1226.72  1143.4 1231.52
#Mann= 3 , 0 , 0
       0     0.1       0   675.7   0.045       0   690.7     0.1       0
Bank Sta=   675.7,   690.7
Exp/Cntr=0.3,0.1

Type RM Length L Ch R = 1 ,3491.1,405.175,400,394.152
XS GIS Cut Line= 3
     1704191.542      392695.805     1703737.792      392662.030
     1703284.207      392626.184
#Sta/Elev= 30
       0 1183.55     9.7 1178.17    19.4 1176.05    48.4 1163.69    67.8 1153.33
    77.4 1151.00   183.9 1104.20   232.3 1086.65   251.7 1077.48   309.8 1055.12
   319.5 1053.57   447.5 1055.02   462.5 1056.31   474.4 1059.21   493.7 1073.17
   503.4 1075.80   522.8 1086.38   532.5 1088.49   551.8 1100.09   561.5 1102.65
   580.9 1114.51   590.5 1117.79   609.9 1128.95   619.6 1131.97   638.9 1143.29
   687.3 1162.18   745.4 1189.34   764.8 1201.00   890.6 1252.55   910.0 1258.32
#Mann= 3 , 0 , 0
       0     0.1       0   447.5   0.045       0   462.5     0.1       0
Bank Sta=   447.5,   462.5
Exp/Cntr=0.3,0.1

Type RM Length L Ch R = 1 ,3091.1,400.412,400.003,392.113
XS GIS Cut Line= 3
     1704135.418      392192.383     1703685.407      392284.025
     1703237.622      392378.748
#Sta/Elev= 30
       0 1128.29    19.5 1121.03    58.6 1109.39    78.2 1101.66   146.6 1081.75
   263.8 1059.23   322.4 1055.29   451.7 1049.85   459.2 1049.81   466.7 1051.07
   478.7 1055.73   507.9 1070.90   517.7 1074.11   537.2 1086.52   585.8 1110.16
   605.3 1122.25   615.1 1124.88   624.8 1130.63   644.3 1139.39   663.7 1151.42
   673.5 1154.72   693.0 1165.41   790.3 1207.49   800.1 1210.81   819.6 1221.13
   829.3 1223.86   848.8 1234.44   878.0 1246.09   907.2 1254.16   916.9 1255.22
#Mann= 3 , 0 , 0
       0     0.1       0   451.7   0.045       0   466.7     0.1       0
Bank Sta=   451.7,   466.7
Exp/Cntr=0.3,0.1

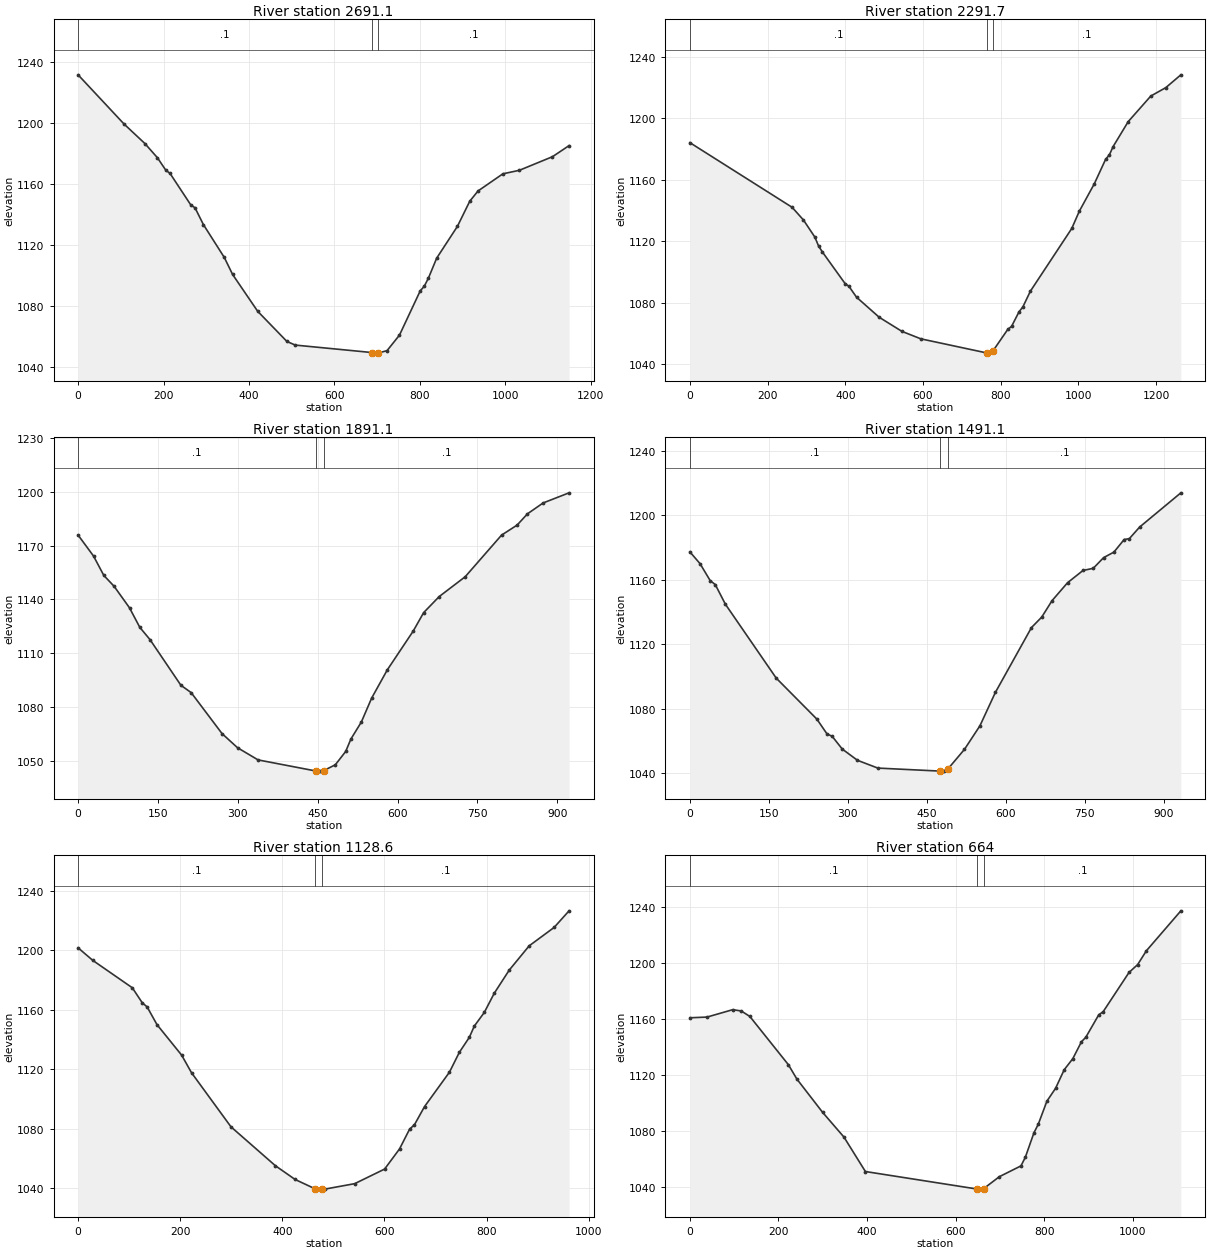
Type RM Length L Ch R = 1 ,2691.1,395.152,399.359,410.738
XS GIS Cut Line= 3
     1704222.044      391756.200     1703545.907      391914.195
     1703160.673      392156.713
#Sta/Elev= 30
       0 1231.66   107.6 1199.37   156.5 1186.53   185.8 1177.22   205.4 1169.04
   215.2 1166.97   264.0 1146.21   273.8 1144.37   293.4 1133.35   342.3 1111.79
   361.8 1100.60   420.5 1076.43   489.0 1056.61   508.5 1054.24   687.1 1049.37
   694.4 1048.96   702.1 1048.97   723.4 1050.59   752.5 1060.78   800.9 1089.73
   810.6 1092.91   820.3 1098.20   839.6 1111.30   888.1 1132.15   917.1 1148.69
   936.5 1155.43   994.6 1166.67  1033.3 1168.99  1110.8 1177.92  1149.6 1185.19
#Mann= 3 , 0 , 0
       0     0.1       0   687.1   0.045       0   702.1     0.1       0
Bank Sta=   687.1,   702.1
Exp/Cntr=0.3,0.1

Type RM Length L Ch R = 1 ,2291.7,413.982,400.637,393.766
XS GIS Cut Line= 3
     1704175.270      391545.720     1703415.254      391554.307
     1702912.389      391580.800
#Sta/Elev= 30
       0 1184.17   263.1 1142.09   292.3 1133.83   321.6 1122.71   331.3 1116.86
   341.1 1112.99   399.5 1092.44   409.3 1090.69   428.8 1083.62   487.2 1070.54
   545.7 1061.36   594.4 1056.50   764.4 1047.30   769.7 1047.20   779.4 1048.42
   818.2 1062.67   827.9 1064.61   847.2 1074.15   856.9 1077.24   876.3 1087.51
   982.8 1128.32  1002.2 1139.54  1040.9 1157.43  1069.9 1173.31  1079.6 1176.23
  1089.3 1181.64  1128.1 1197.86  1186.2 1214.50  1224.9 1219.99  1263.6 1228.31
#Mann= 3 , 0 , 0
       0     0.1       0   764.4   0.045       0   779.4     0.1       0
Bank Sta=   764.4,   779.4
Exp/Cntr=0.3,0.1

Type RM Length L Ch R = 1 ,1891.1,391.096,400,396.273
XS GIS Cut Line= 3
     1703688.925      390909.020     1703320.291      391173.787
     1702888.971      391355.976
#Sta/Elev= 30
       0 1175.83    29.0 1164.16    48.3 1153.38    67.6 1147.33    96.6 1135.32
   115.9 1124.46   135.2 1117.57   193.1 1092.20   212.4 1088.11   270.4 1065.28
   299.4 1057.44   338.0 1050.65   446.4 1044.48   453.9 1044.40   461.4 1044.71
   483.1 1047.93   502.6 1055.36   512.4 1062.29   531.9 1071.69   551.4 1085.10
   580.7 1100.77   629.4 1122.39   649.0 1132.66   678.2 1141.60   727.0 1152.63
   795.3 1175.81   824.5 1181.39   844.0 1187.67   873.3 1193.71   922.1 1199.36
#Mann= 3 , 0 , 0
       0     0.1       0   446.4   0.045       0   461.4     0.1       0
Bank Sta=   446.4,   461.4
Exp/Cntr=0.3,0.1

Type RM Length L Ch R = 1 ,1491.1,365.337,362.521,366.421
XS GIS Cut Line= 3
     1703597.903      390717.825     1703128.846      390830.719
     1702738.460      391055.072
#Sta/Elev= 30
       0 1177.39    19.3 1170.06    38.6 1159.53    48.2 1157.11    67.5 1144.88
   164.0 1099.07   241.2 1073.65   260.5 1064.44   270.2 1063.00   289.5 1055.04
   318.4 1048.08   357.0 1043.26     475 1041.39   482.5 1041.37     490 1042.64
   521.6 1054.87   551.0 1069.50   580.3 1090.18   648.9 1130.43   668.4 1136.92
   688.0 1147.13   717.4 1158.23   746.7 1165.83   766.3 1167.20   785.9 1173.80
   805.5 1177.24   825.0 1185.05   834.8 1185.58   854.4 1192.79   932.7 1214.01
#Mann= 3 , 0 , 0
       0     0.1       0     475   0.045       0     490     0.1       0
Bank Sta=     475,     490
Exp/Cntr=0.3,0.1

Type RM Length L Ch R = 1 ,1128.6,458.85,464.548,411.397
XS GIS Cut Line= 3
     1703547.238      390331.562     1703123.705      390520.034
     1702662.043      390706.504
#Sta/Elev= 30
       0 1201.55    29.0 1193.07   106.2 1174.71   125.6 1164.66   135.2 1161.86
   154.5 1149.95   202.8 1129.44   222.1 1117.64   299.4 1081.27   386.3 1055.15
   424.9 1045.91   463.4 1039.73   478.4 1039.42   483.1 1039.40   541.7 1043.07
   600.3 1052.89   629.5 1066.42   649.1 1079.63   658.8 1082.72   678.4 1094.84
   727.2 1117.98   746.7 1131.37   766.2 1141.42   776.0 1149.01   795.5 1158.15
   815.0 1171.05   844.3 1186.58   883.4 1202.91   932.2 1215.26   961.5 1226.43
#Mann= 3 , 0 , 0
       0     0.1       0   463.4   0.045       0   478.4     0.1       0
Bank Sta=   463.4,   478.4
Exp/Cntr=0.3,0.1

Type RM Length L Ch R = 1 ,664,426.416,424.072,420.158
XS GIS Cut Line= 3
     1703520.443      390177.599     1703126.277      390135.474
     1702556.533      390563.378
#Sta/Elev= 30
       0 1160.78    38.7 1161.28    96.7 1166.55   116.0 1165.63   135.4 1161.73
   222.4 1127.37   241.7 1117.10   299.7 1093.43   348.1 1075.72   396.4 1051.24
   648.8 1038.76   650.2 1038.70   663.8 1039.13   699.0 1047.58   747.8 1055.27
   757.6 1061.39   777.1 1078.86   786.8 1084.89   806.4 1101.41   825.9 1110.52
   845.4 1123.76   864.9 1131.68   884.4 1143.72   894.2 1146.89   923.5 1162.94
   933.3 1165.06   991.8 1193.07  1011.3 1198.67  1030.9 1208.48  1108.9 1236.98
#Mann= 3 , 0 , 0
       0     0.1       0   648.8   0.045       0   663.8     0.1       0
Bank Sta=   648.8,   663.8
Exp/Cntr=0.3,0.1

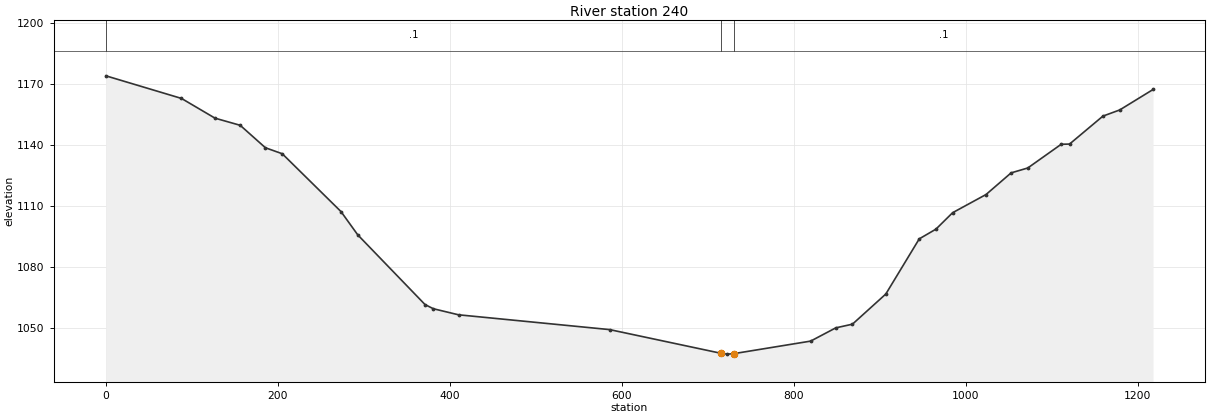
Type RM Length L Ch R = 1 ,240,217.006,239.955,264.474
XS GIS Cut Line= 3
     1703251.496      389452.611     1702713.602      389920.345
     1702374.495      390294.532
#Sta/Elev= 30
       0 1174.07    87.9 1162.96   126.9 1153.26   156.2 1149.75   185.5 1138.72
   205.1 1135.77   273.4 1107.35   292.9 1095.90   371.1 1061.66   380.8 1059.59
   410.1 1056.61   585.9 1049.33   714.9 1037.73   722.5 1037.28   729.9 1037.49
   819.6 1043.68   848.8 1050.19   868.2 1052.00   907.0 1066.82   945.9 1093.94
   965.3 1098.71   984.7 1106.79  1023.6 1115.74  1052.7 1126.36  1072.1 1128.77
  1111.0 1140.43  1120.7 1140.53  1159.5 1154.27  1179.0 1157.29  1217.8 1167.35
#Mann= 3 , 0 , 0
       0     0.1       0   714.9   0.045       0   729.9     0.1       0
Bank Sta=   714.9,   729.9
Exp/Cntr=0.3,0.1